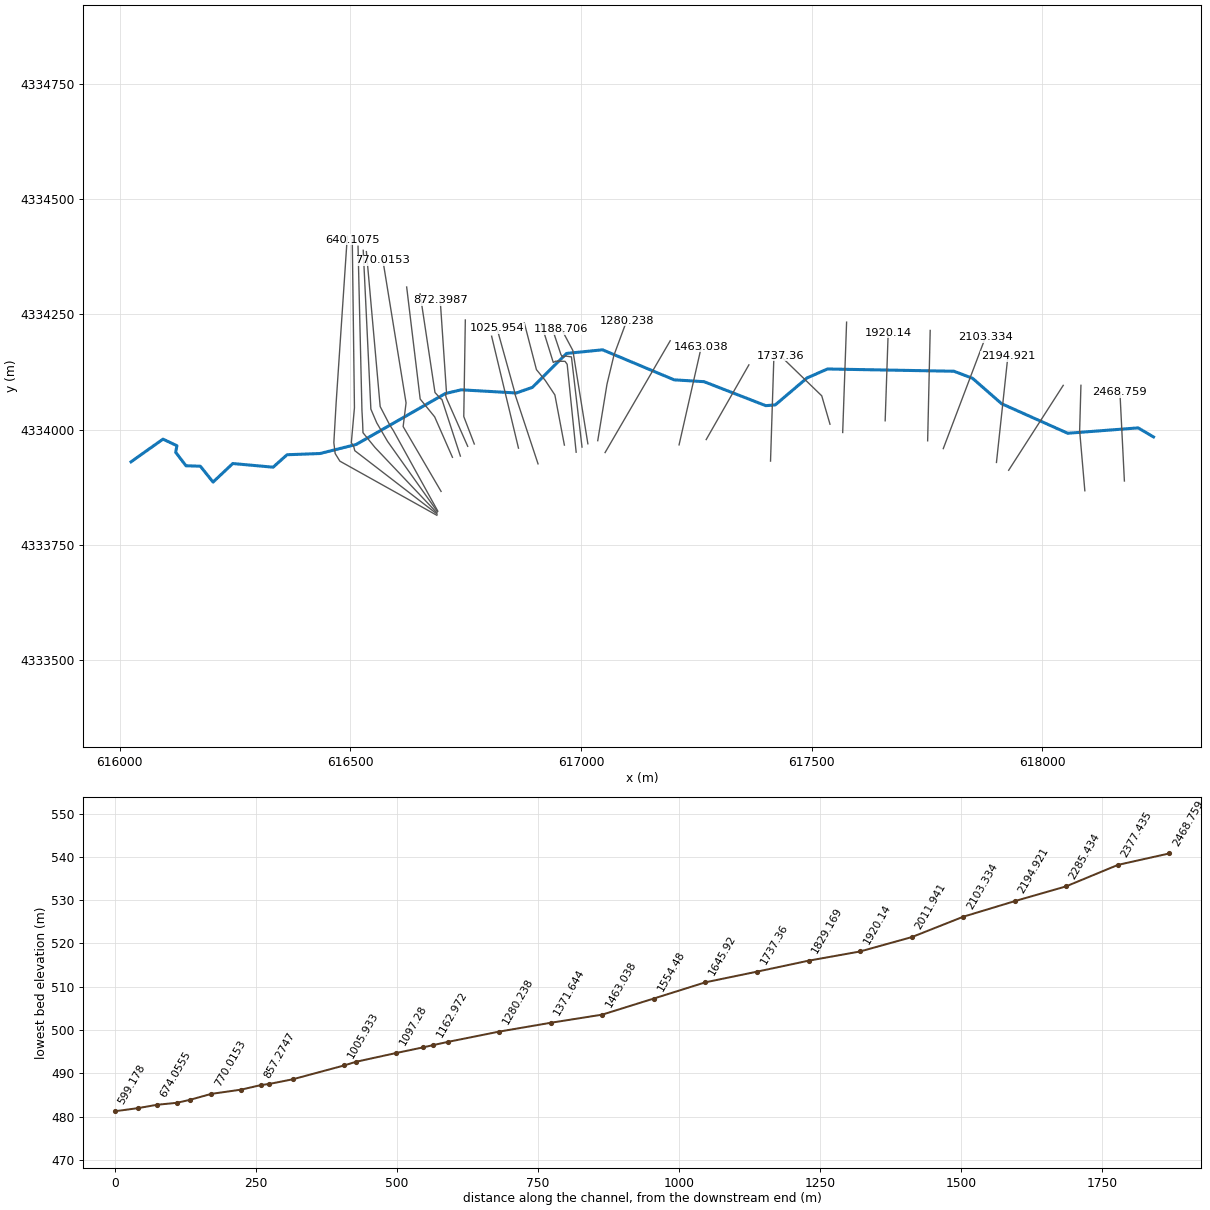
--- DryRun.prj (project) ---

Proj Title=DryRun
Current Plan=p01
Default Exp/Contr=0.3,0.1
SI Units
Geom File=g01
Flow File=f01
Plan File=p01
Background Map Layer=Google Hybrid
Y Axis Title=Elevation
X Axis Title(PF)=Main Channel Distance
X Axis Title(XS)=Station
BEGIN DESCRIPTION:
September 2018
Tucker County ABFE Study
US Army Corps of Engineers, Pittsburgh District
NAD 1983 UTM 17N (meters)
END DESCRIPTION:
DSS Export Rating Curves= 0
DSS Export Rating Curve Sorted= 0
DSS Export Volume Flow Curves= 0
DXF OffsetX= 0
DXF OffsetY= 0
DXF ScaleX= 1
DXF ScaleY= 10

--- DryRun.p01 (plan) ---

Plan Title=DryRun_plan
Program Version=5.05
Short Identifier=Plan1_subcritical
Geom File=g01
Flow File=f01
Subcritical Flow
K Sum by GR= 0
Std Step Tol= 0.003
Critical Tol= 0.003
Num of Std Step Trials= 20
Max Error Tol= 0.1
Flow Tol Ratio= 0.001
Split Flow NTrial= 30
Split Flow Tol= 0.006
Split Flow Ratio= 0.02
Log Output Level= 0
Friction Slope Method= 1
Unsteady Friction Slope Method= 2
Unsteady Bridges Friction Slope Method= 1
Parabolic Critical Depth
Global Vel Dist= 0 , 0 , 0
Global Log Level= 0
CheckData=True
Encroach Param=-1 ,0,0, 0
Computation Interval=1MIN
Output Interval=1HOUR
Instantaneous Interval=1HOUR
Mapping Interval=1HOUR
Computation Time Step Use Courant=        0
Computation Time Step Use Time Series=    0
Computation Time Step Count To Double=0
Computation Time Step Max Doubling=0
Computation Time Step Max Halving=0
Computation Time Step Residence Courant=0
Run HTab= 0
Run UNet= 0
Run Sediment= 0
Run PostProcess= 0
Run WQNet= 0
Run RASMapper=-1
UNET Theta= 1
UNET Theta Warmup= 1
UNET ZTol= 0.006
UNET ZSATol= 0.006
UNET MxIter= 20
UNET Max Iter WO Improvement= 0
UNET MaxInSteps= 0
UNET DtIC= 0
UNET DtMin= 0
UNET MaxCRTS= 20
UNET WFStab= 2
UNET SFStab= 1
UNET WFX= 1
UNET SFX= 1
UNET 1D Methodology=Finite Difference
UNET DSS MLevel= 4
UNET Pardiso=0
UNET DZMax Abort= 30
UNET Use Existing IB Tables=-1
UNET Froude Reduction=False
UNET Froude Limit= 0.8
UNET Froude Power= 4
UNET D1 Cores= 0
UNET D2 Coriolis=0
UNET D2 Cores= 0
UNET D2 Theta= 1
UNET D2 Theta Warmup= 1
UNET D2 Z Tol= 0.003
UNET D2 Volume Tol= 0.003
UNET D2 Max Iterations= 20
UNET D2 Equation= 0
UNET D2 RampUpFraction=0.1
UNET D2 TimeSlices= 1
UNET D2 BCVolumeCheck=0
UNET D1D2 MaxIter= 0
UNET D1D2 ZTol=0.003
UNET D1D2 QTol=0.1
UNET D1D2 MinQTol=0.03
Write IC File= 0
Write IC File at Fixed DateTime=0
Write IC File at Sim End=0
Echo Input=False
Echo Parameters=False
Echo Output=False
Write Detailed= 0
HDF Write Warmup=0
HDF Write Time Slices=0
HDF Flush=0
HDF Face Node Velocities=0
HDF Compression= 1
HDF Chunk Size= 1
HDF Spatial Parts= 1
HDF Use Max Rows=0
HDF Fixed Rows= 1
Calibration Method= 0
Calibration Iterations= 20
Calibration Max Change=0.05
Calibration Tolerance=0.2
Calibration Maximum=1.5
Calibration Minimum=0.5
Calibration Optimization Method= 1
WQ AD Non Conservative
WQ ULTIMATE=-1
WQ Max Comp Step=1HOUR
WQ Output Interval=15MIN
WQ Output Selected Increments= 0
WQ Output face flow=0
WQ Output face velocity=0
WQ Output face area=0
WQ Output face dispersion=0
WQ Output cell volume=0
WQ Output cell surface area=0
WQ Output cell continuity=0
WQ Output cumulative cell continuity=0
WQ Output face conc=0
WQ Output face dconc_dx=0
WQ Output face courant=0
WQ Output face peclet=0
WQ Output face adv mass=0
WQ Output face disp mass=0
WQ Output cell mass=0
WQ Output cell source sink temp=0
WQ Output nsm pathways=0
WQ Output nsm derived pathways=0
WQ Output MaxMinRange=-1
WQ Daily Max Min Mean=-1
WQ Daily Range=0
WQ Daily Time=0
WQ Create Restart=0
WQ Fixed Restart=0
WQ System Summary=0
WQ Write To DSS=0
WQ Use Fixed Temperature=0
Sorting and Armoring Iterations= 10
XS Update Threshold= 0.02
Bed Roughness Predictor= 0
Hydraulics Update Threshold= 0.02
Energy Slope Method= 1
Volume Change Method= 1
Sediment Retention Method= 0
XS Weighting Method= 0
Number of US Weighted Cross Sections= 1
Number of DS Weighted Cross Sections= 1
Upstream XS Weight=0
Main XS Weight=1
Downstream XS Weight=0
Number of DS XS's Weighted with US Boundary= 1
Upstream Boundary Weight= 1
Weight of XSs Associated with US Boundary= 0
Number of US XS's Weighted with DS Boundary= 1
Downstream Boundary Weight= 0.5
Weight of XSs Associated with DS Boundary= 0.5
Percentile Method= 0
Sediment Output Level= 4
Mass or Volume Output= 0
Output Increment Type= 1
Profile and TS Output Increment= 1
XS Output Flag= 0
XS Output Increment= 10
Write Gradation File= 0
Read Gradation Hotstart= 0
Write HDF5 File= 1
Write Binary Output= 1
Write DSS Sediment File= 0
SV Curve= 0
Specific Gage Flag= 0

--- DryRun.f01 (steady flow) ---

Flow Title=DryRun_flow
Program Version=5.05
Number of Profiles= 1
Profile Names=PF 1
River Rch & RM=Dry Run,1               ,2468.759
   14.64
River Rch & RM=Dry Run,1               ,1144.899
 16.0272
River Rch & RM=Dry Run,1               ,365.76
 16.5652
Boundary for River Rch & Prof#=Dry Run,1               , 1
Up Type= 2
Dn Type= 1
Dn Known WS=479.1
DSS Import GetInterval= 0
DSS Import GetPeak= 0
DSS Import FillOption= 0

--- DryRun.g01 (geometry) ---

Geom Title=DryRun_geometry
Program Version=5.05

River Reach=Dry Run         ,1
Reach XY= 30
     618240.6082    4333984.3875     618207.2706    4334003.9667
     618054.7644     4333992.325     617911.4658    4334056.3543
     617848.4949    4334111.3877     617808.2781    4334126.7336
      617533.948    4334131.6392617489.7671824364334112.29289391
617420.7461381734334053.75570305617400.2342381734334052.17054426
     617266.3442    4334104.1778617201.8191824364334108.07378853
     617046.4394     4334173.219     616968.4889    4334165.3629
     616894.4055    4334091.8085     616859.4804    4334079.6377
     616739.8885    4334086.5169616705.5628764474334078.33840224
616512.3435114734333967.98386183     616434.0295    4333948.4041
     616362.5919    4333945.7582     616332.4293    4333918.7707
     616244.9844    4333926.7082     616202.2541    4333886.4915
     616174.7374    4333920.8874     616143.5165    4333921.9457
     616121.2914    4333951.0499     616123.9373    4333965.3375
     616093.7747     4333979.625     616024.4537    4333930.4124

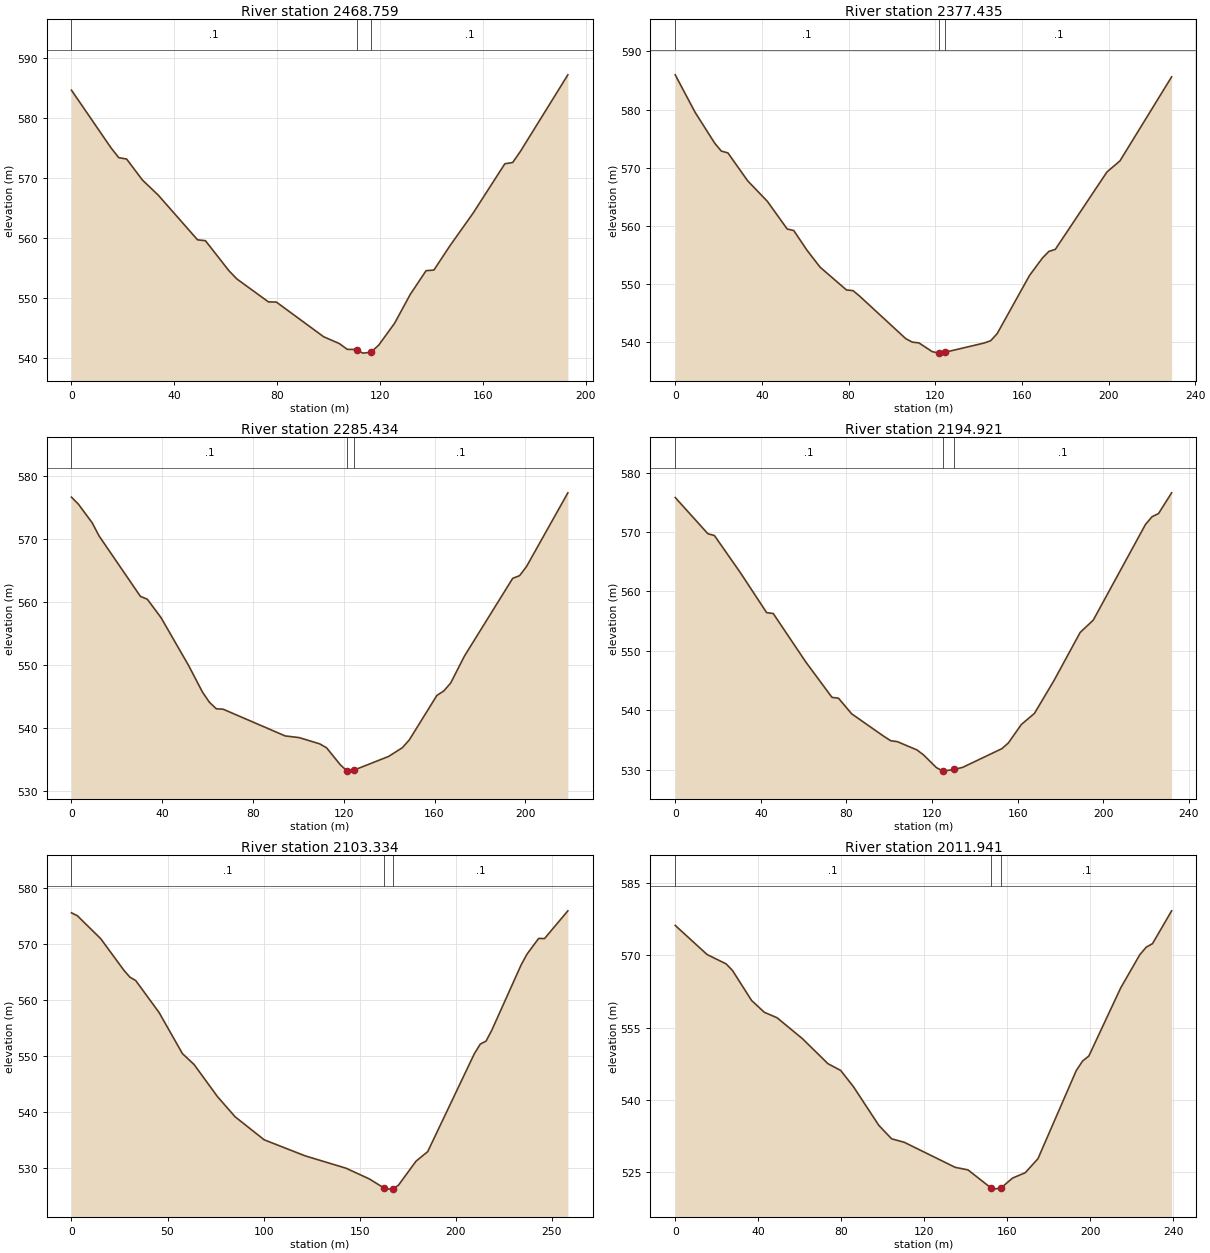
Type RM Length L Ch R = 1 ,2468.759,91.12,91.32,91.22
XS GIS Cut Line= 2
     618177.5232    4333888.8512     618167.8066    4334081.5682
#Sta/Elev= 30
       0  584.56   15.31     575   18.38  573.33   21.44   573.1   27.57  569.61
   33.69  567.11   49.01  559.65   52.07  559.51   61.26  554.48   64.32  553.13
   76.57  549.32   79.64  549.29   98.01  543.52  104.14  542.38   107.2  541.42
  110.26   541.4  110.92  541.27  113.33  540.79  116.39  540.93  119.45  542.13
  125.58  545.75   131.7  550.57  137.83  554.51  140.89  554.62  147.02   558.6
  156.21  564.15  168.46  572.31  171.52  572.53  174.58  574.42  192.96  587.12
#Mann= 3 , 0 , 0
       0      .1       0  110.92      .1       0  116.39      .1       0
Bank Sta=110.92,116.39
XS Rating Curve= 0 ,0
Exp/Cntr=0.3,0.1

Type RM Length L Ch R = 1 ,2377.435,96.14,92,86.4
XS GIS Cut Line= 3
     618091.7981    4333867.6845     618080.5386    4333997.9132
     618083.3314    4334096.2849
#Sta/Elev= 30
       0  585.98    9.12  579.57   18.24  574.22   21.28  572.87   24.32  572.56
   33.44  567.76   42.56  564.22   51.68  559.48   54.72  559.21    60.8  555.84
   66.88  552.91   79.04     549   82.08  548.88   85.12  547.94   106.4  540.63
  109.44  540.03  112.48   539.9  118.56  538.41  121.59  538.14  124.63   538.3
  142.64  539.88  145.63  540.28  148.61  541.49  163.52  551.48  169.48  554.48
  172.46  555.62  175.45  555.98   199.3  569.29  205.27  571.18  229.13  585.63
#Mann= 3 , 0 , 0
       0      .1       0  121.59      .1       0  124.63      .1       0
Bank Sta=121.59,124.63
XS Rating Curve= 0 ,0
Exp/Cntr=0.3,0.1

Type RM Length L Ch R = 1 ,2285.434,87.52,90.51,92.75
XS GIS Cut Line= 2
     617926.6977    4333912.1346     618044.9696    4334096.1669
#Sta/Elev= 30
       0  576.62    3.04  575.52    9.12  572.56   12.15  570.48   30.38  560.89
   33.42  560.44    39.5   557.5   51.65  549.91   57.73  545.71   60.77  544.11
   63.81  543.07   66.84     543   94.19  538.76  100.27   538.5  109.38  537.51
  112.42  536.88   118.5  534.18  121.53  533.18  124.57  533.35  139.76  535.51
  145.84   536.9  148.88  538.13  161.03  545.18  164.07  545.89  167.11  547.15
  173.19  551.43  194.45  563.75  197.49  564.18  200.53  565.62  218.76  577.31
#Mann= 3 , 0 , 0
       0      .1       0  121.53      .1       0  124.57      .1       0
Bank Sta=121.53,124.57
XS Rating Curve= 0 ,0
Exp/Cntr=0.3,0.1

Type RM Length L Ch R = 1 ,2194.921,101.8,91.59,90.48
XS GIS Cut Line= 2
     617900.2393    4333929.0679     617925.0463    4334159.6158
#Sta/Elev= 30
       0   575.8   15.26  569.71   18.31  569.41   30.51  563.12   42.71  556.44
   45.77   556.3   61.02  548.13   73.22   542.2   76.28  542.05   82.38  539.44
   97.63   535.6  100.68   534.9  103.74  534.75  112.89  533.36  115.94  532.54
  122.04  530.37  125.09  529.79  130.25  530.08  134.25  530.42  152.55  533.56
   155.6  534.52   161.7  537.64  167.81   539.5  176.96  545.04  189.16  553.11
  195.27  555.18  219.67  571.27  222.73  572.57  225.78  573.11  231.88  576.59
#Mann= 3 , 0 , 0
       0      .1       0  125.09      .1       0  130.25      .1       0
Bank Sta=125.09,130.25
XS Rating Curve= 0 ,0
Exp/Cntr=0.3,0.1

Type RM Length L Ch R = 1 ,2103.334,88.46,91.39,92.76
XS GIS Cut Line= 2
      617784.969    4333959.0541     617876.5187    4334200.6399
#Sta/Elev= 30
       0  575.64    3.04  575.13    15.2  571.02   27.35  565.33   30.39  564.13
   33.43  563.52   45.59   557.8   57.75  550.44   63.83  548.48   75.99  542.74
    85.1  539.15   100.3  535.01  121.58  532.14  142.85  529.93  155.01  528.01
  162.47  526.42  164.13  526.18  167.47  526.25  170.21   526.9  179.33  531.19
   185.4  532.89  209.72  550.45  212.76  552.14   215.8  552.69  218.84  554.69
  234.04  566.33  237.07  568.24  243.15  571.06  246.19  571.03  258.35     576
#Mann= 3 , 0 , 0
       0      .1       0  162.47      .1       0  167.47      .1       0
Bank Sta=162.47,167.47
XS Rating Curve= 0 ,0
Exp/Cntr=0.3,0.1

Type RM Length L Ch R = 1 ,2011.941,91.96,91.8,91.76
XS GIS Cut Line= 2
     617751.1022    4333975.9875     617756.6202     4334215.193
#Sta/Elev= 30
       0  576.23   15.34  570.19   24.54  568.24   27.61  566.87   36.81  560.64
   42.95  558.19   49.08  557.06   61.35   552.7   73.62  547.52   79.76  546.11
   85.89  542.75   98.16   534.7   104.3  531.92  110.43  531.19  134.97  525.99
  141.11  525.47  151.99  521.79  153.38  521.47  156.99   521.7  162.58  523.76
  168.72  524.88  174.85  527.79  193.26  546.05  196.32  548.05  199.39  549.12
  214.73  563.26  223.93  570.14     227   571.7  230.07  572.45  239.27  579.26
#Mann= 3 , 0 , 0
       0      .1       0  151.99      .1       0  156.99      .1       0
Bank Sta=151.99,156.99
XS Rating Curve= 0 ,0
Exp/Cntr=0.3,0.1

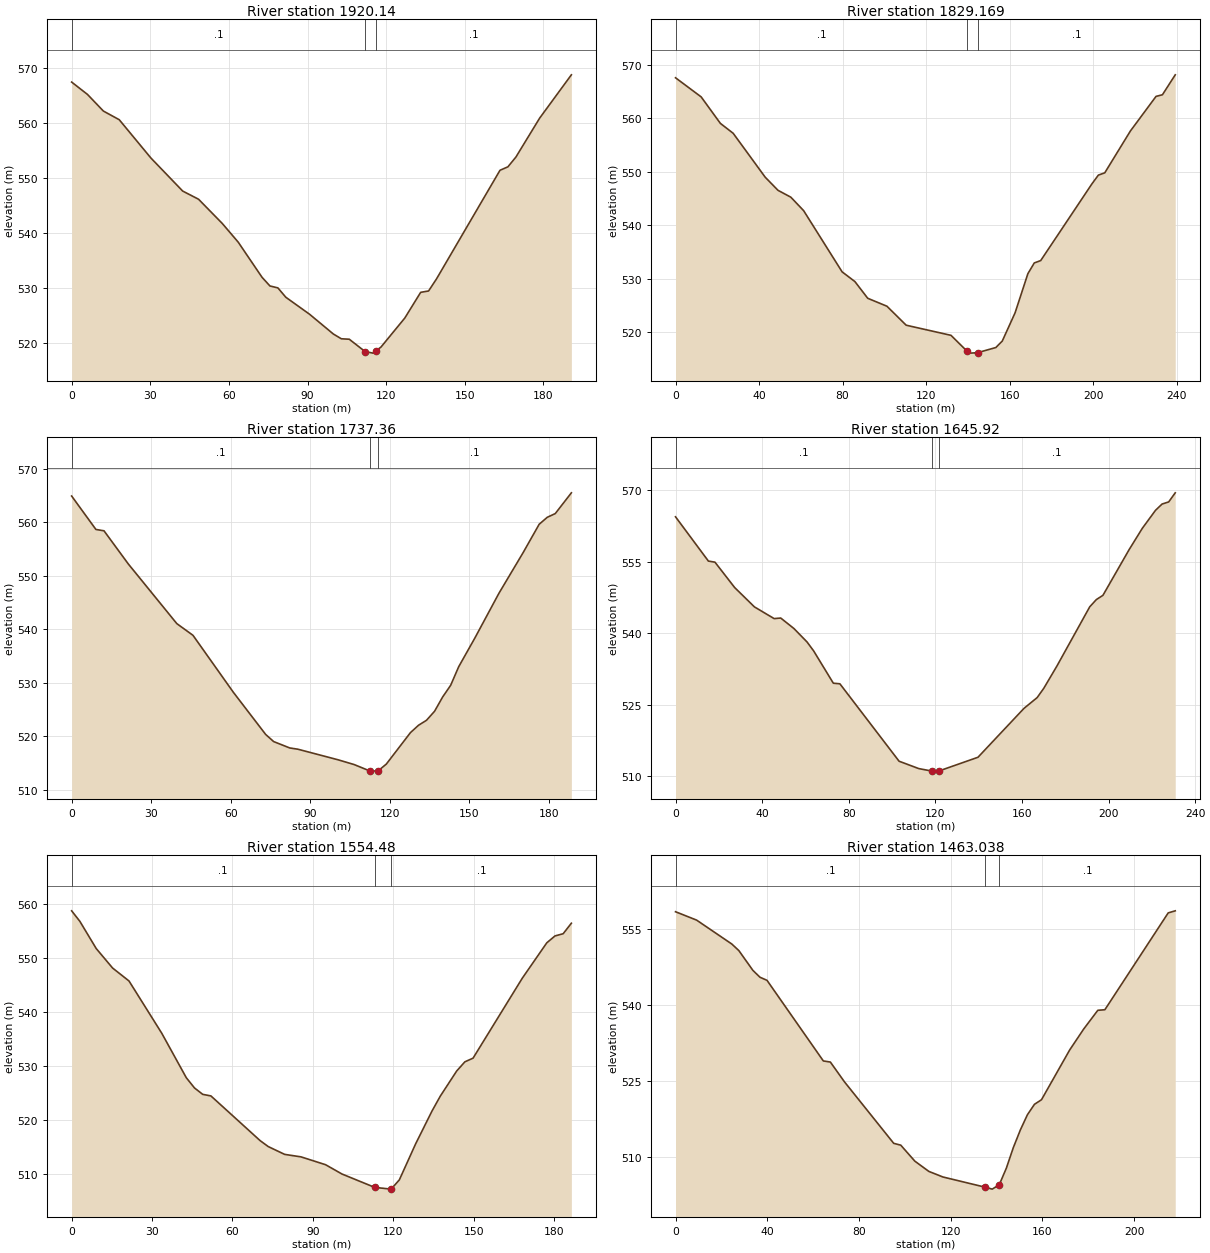
Type RM Length L Ch R = 1 ,1920.14 ,91,90.97,90.97
XS GIS Cut Line= 2
     617659.0271    4334019.3792     617665.5221    4334209.9095
#Sta/Elev= 30
       0  567.47    6.05  565.22    12.1   562.2   18.16  560.62   30.26  553.64
   42.36  547.64   48.42  546.15   57.49  541.73   63.55  538.34   72.63  531.95
   75.65  530.37   78.68  530.02    81.7  528.32   90.78  525.22   99.86  521.62
  102.89  520.76  105.91  520.68  111.96  518.43  114.99  518.15  116.23  518.61
  118.02  519.26  127.09  524.53  133.15  529.21  136.17  529.46   139.2  531.66
  163.41  551.42  166.43  552.05  169.46  553.81  178.54  560.91  190.64  568.79
#Mann= 3 , 0 , 0
       0      .1       0  111.96      .1       0  116.23      .1       0
Bank Sta=111.96,116.23
XS Rating Curve= 0 ,0
Exp/Cntr=0.3,0.1

Type RM Length L Ch R = 1 ,1829.169,82.15,91.81,95.18
XS GIS Cut Line= 2
     617566.9519    4333993.9792     617575.4186     4334233.163
#Sta/Elev= 30
       0  567.59   12.27  564.01   21.48  559.05   27.62  557.19   42.96  548.97
   49.09  546.51   55.23  545.23   61.37   542.7   79.78  531.25   85.91  529.43
   92.05   526.3  101.26  524.81  110.46  521.26  131.94  519.36  139.63  516.39
  141.15  516.03  144.63  516.11  153.42  517.08  156.49  518.29  162.62  523.57
  168.76  530.91  171.83  532.92   174.9  533.36  199.44  547.73  202.51  549.36
  205.58  549.79  217.85  557.62  230.13   564.1   233.2  564.41  239.33  568.14
#Mann= 3 , 0 , 0
       0      .1       0  139.63      .1       0  144.63      .1       0
Bank Sta=139.63,144.63
XS Rating Curve= 0 ,0
Exp/Cntr=0.3,0.1

Type RM Length L Ch R = 1 ,1737.36 ,98.96,91.44,88.04
XS GIS Cut Line= 3
     617539.4352    4334011.9709     617521.5564     4334073.471
     617432.2291     4334160.007
#Sta/Elev= 30
       0  564.92    9.15  558.67    12.2  558.42   21.35  552.23   39.65  541.07
   45.75  538.88      61  528.21   73.15  520.35   76.18  519.01   82.25  517.82
   85.28  517.59  100.45  515.61  106.51  514.72  112.58  513.49  115.61  513.56
  118.65  514.81  127.75  520.69  130.78  522.06  133.81     523  136.85  524.69
  139.88  527.35  142.91  529.54  145.95  533.02  152.02  538.36  161.12  546.75
  170.22  554.33  176.28  559.64  179.32  560.94  182.35  561.64  188.42  565.52
#Mann= 3 , 0 , 0
       0      .1       0  112.58      .1       0  115.61      .1       0
Bank Sta=112.58,115.61
XS Rating Curve= 0 ,0
Exp/Cntr=0.3,0.1

Type RM Length L Ch R = 1 ,1645.92 ,96.1,91.44,89.48
XS GIS Cut Line= 2
     617410.5452    4333931.9731     617417.9863    4334162.6551
#Sta/Elev= 30
       0  564.39   15.18   555.1   18.22  554.87   27.33  549.54   36.44  545.49
   45.55  543.03   48.59  543.15   54.66  540.96   60.74  538.13   63.77  536.27
   72.88  529.48   75.92  529.35  103.25  513.11  112.36  511.56  118.44  511.04
  121.47  511.03   139.7  513.94  160.95   524.2  167.03  526.46  170.06  528.39
  176.14  533.07  191.32  545.51  194.36  547.02   197.4  547.91  209.54  557.53
  215.62  561.99  221.69  565.75  224.73  567.07  227.77  567.51   230.8  569.42
#Mann= 3 , 0 , 0
       0      .1       0  118.44      .1       0  121.47      .1       0
Bank Sta=118.44,121.47
XS Rating Curve= 0 ,0
Exp/Cntr=0.3,0.1

Type RM Length L Ch R = 1 ,1554.48 ,87.68,91.44,92.8
XS GIS Cut Line= 2
      617271.123    4333978.6698     617363.6379    4334140.5706
#Sta/Elev= 30
       0  558.71    3.06  556.77    9.17  551.74   15.28  548.14    21.4  545.75
   33.63  536.09    42.8  527.86   45.85  525.98   48.91   524.8   51.97  524.51
   70.31  516.26   73.37  515.15   79.48  513.71   85.59  513.25   94.76   511.8
  100.88  510.08   113.1  507.61  119.22  507.29  122.28     509  128.39  515.69
   134.5  521.75  137.56  524.47  143.67  529.11  146.73  530.81  149.79  531.49
  168.13  546.24   177.3   552.8  180.36  554.07  183.41  554.48  186.47  556.42
#Mann= 3 , 0 , 0
       0      .1       0   113.1      .1       0  119.22      .1       0
Bank Sta=113.1,119.22
XS Rating Curve= 0 ,0
Exp/Cntr=0.3,0.1

Type RM Length L Ch R = 1 ,1463.038,94.63,91.39,90.17
XS GIS Cut Line= 2
     617212.3037    4333967.1504     617260.5764    4334179.7287
#Sta/Elev= 30
       0  558.45    9.21  556.79   24.56  552.06   27.63  550.76   33.77  546.84
   36.84  545.49   39.91  544.88   64.48  528.93   67.55  528.71   73.69   524.8
   95.18  512.63   98.25  512.27  104.39  509.11  110.53  507.07  116.67  505.97
  135.09  503.95  138.16  503.57  141.23  504.44   144.3   507.7  147.37   511.8
  150.44  515.29  153.51  518.29  156.58  520.35  159.65  521.26  171.94   531.1
  178.08  535.26  184.22  538.95  187.29  539.06  214.92  558.22  217.99  558.63
#Mann= 3 , 0 , 0
       0      .1       0  135.09      .1       0  141.23      .1       0
Bank Sta=135.09,141.23
XS Rating Curve= 0 ,0
Exp/Cntr=0.3,0.1

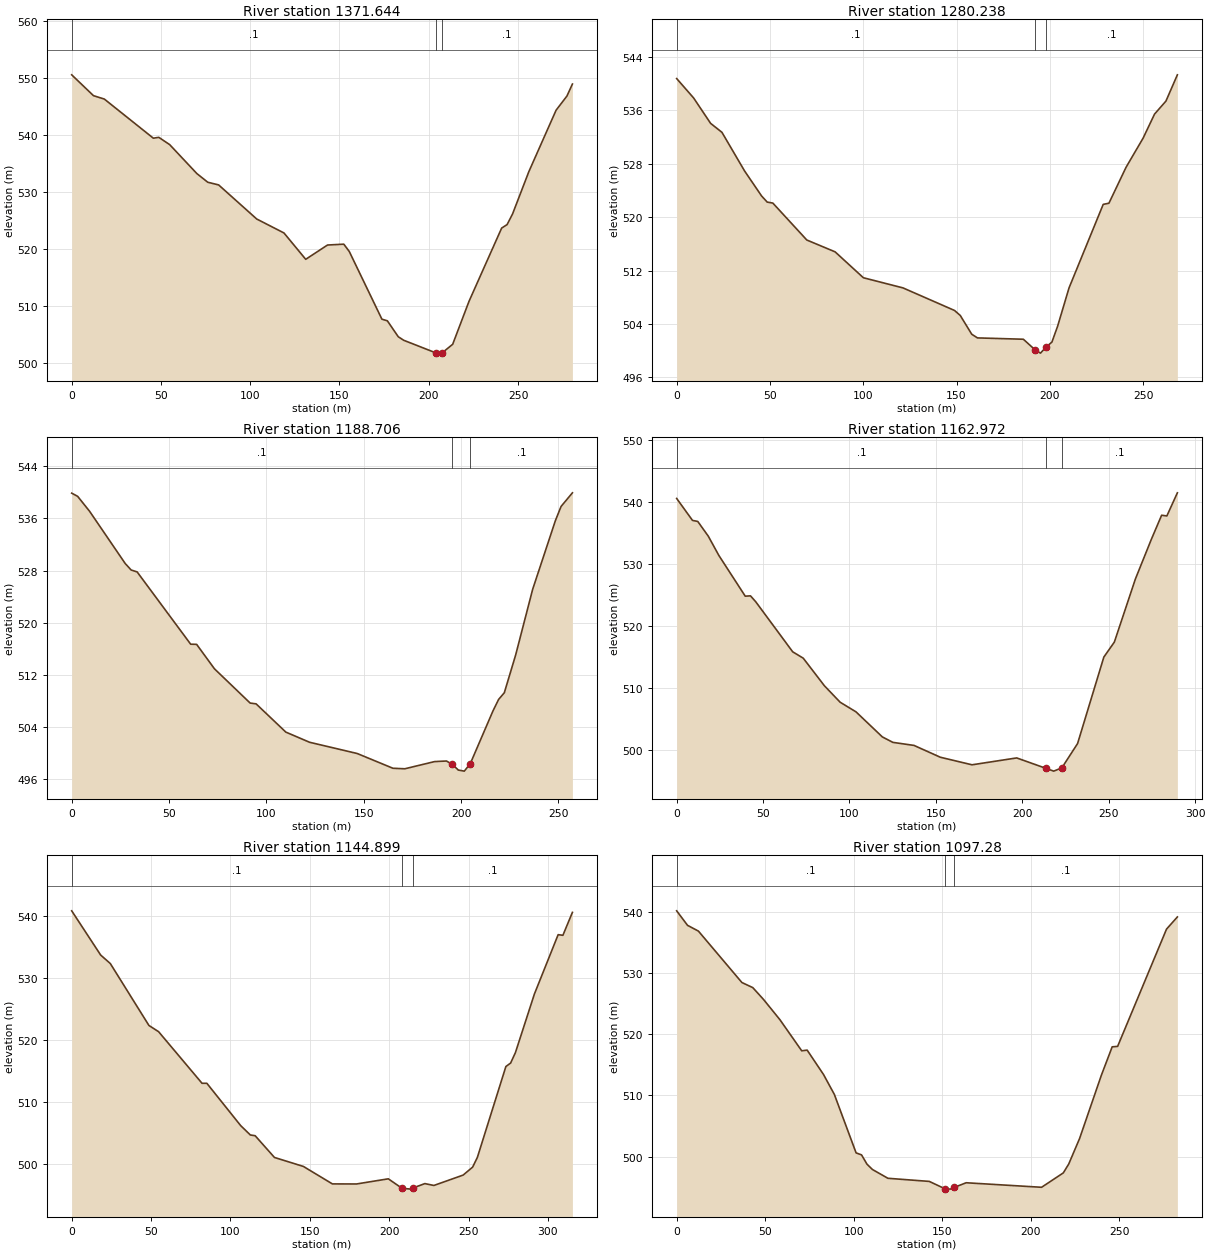
Type RM Length L Ch R = 1 ,1371.644,88.72,91.41,92.1
XS GIS Cut Line= 2
     617051.9658    4333950.4816     617193.1424    4334192.8391
#Sta/Elev= 30
       0  550.58   12.19  546.92   18.29  546.32   45.73  539.45   48.78   539.6
   54.88  538.32   70.12  533.23   76.22  531.71   82.31  531.24  103.65  525.25
   118.9   522.8  131.09  518.17  143.29  520.68  152.43  520.83  155.48  519.55
  173.77  507.65  176.82  507.37  182.92  504.57  185.97  503.95  204.26   501.7
  207.31  501.69  213.41  503.24  222.55  510.78  240.85  523.66  243.89  524.27
  246.94  526.13  256.09  533.58  271.33  544.36  277.43  546.86  280.48  548.96
#Mann= 3 , 0 , 0
       0      .1       0  204.26      .1       0  207.31      .1       0
Bank Sta=204.26,207.31
XS Rating Curve= 0 ,0
Exp/Cntr=0.3,0.1

Type RM Length L Ch R = 1 ,1280.238,84.99,91.53,129.94
XS GIS Cut Line= 4
     617036.0522    4333976.2611     617056.1356    4334098.9434
     617071.2482    4334161.6964     617098.7972    4334236.2322
#Sta/Elev= 30
       0  540.77     9.1  537.86   18.19  534.06   24.26  532.72   36.38  526.94
   45.48   523.2   48.51  522.27   51.55  522.12   69.74  516.59    84.9  514.82
  100.06  510.94  121.28  509.42   148.9  506.04  151.98  505.29  158.13  502.48
   161.2  501.93  185.79  501.73  191.92  500.18  194.97  499.65  198.03  500.58
  201.09   501.3  204.14  503.67  210.26  509.41  228.59  521.93  231.65   522.1
  240.82  527.48  249.99  531.86   256.1  535.45  262.21   537.4  268.33  541.33
#Mann= 3 , 0 , 0
       0      .1       0  191.92      .1       0  198.03      .1       0
Bank Sta=191.92,198.03
XS Rating Curve= 0 ,0
Exp/Cntr=0.3,0.1

Type RM Length L Ch R = 1 ,1188.706,5.25,25.73,27.84
XS GIS Cut Line= 3
     617014.6595    4333969.5316     616982.1457    4334171.6364
     616957.5094    4334217.9759
#Sta/Elev= 30
       0  539.86    3.06  539.37    9.17  537.09    27.5  529.07   30.55  528.08
   33.61  527.79   61.11  516.71   64.16  516.69   73.33  512.94   91.66  507.69
   94.71  507.57  109.99  503.24  122.21  501.68  146.65  499.96  164.98   497.7
   171.1  497.62  186.37  498.72  192.48  498.81  195.54  498.29  198.59  497.42
  201.65  497.26   204.7  498.39  216.37  506.48  219.28  508.25   222.2  509.27
  228.03  515.06  236.78  525.14  248.44  535.65  251.35  537.82  257.18  539.91
#Mann= 3 , 0 , 0
       0      .1       0  195.54      .1       0   204.7      .1       0
Bank Sta=195.54,204.7
XS Rating Curve= 0 ,0
Exp/Cntr=0.3,0.1

Type RM Length L Ch R = 1 ,1162.972,14.98,18.07,23.29
XS GIS Cut Line= 6
     617001.9595    4333962.3879     616979.0449    4334157.8098
     616966.5566    4334159.7148     616960.8416    4334156.9632
     616956.3966    4334162.4665     616935.2844    4334225.9134
#Sta/Elev= 30
       0  540.54    9.16     537   12.21  536.83   18.31  534.45   24.42  531.34
   39.68  524.77   42.73  524.82   45.78  523.86   67.14  515.79   73.25  514.76
   85.46  510.32   94.61  507.65  103.77   506.1  119.03  502.05  125.13  501.17
  137.34  500.68   152.6  498.77  170.91  497.55  196.77  498.66   213.7  496.98
  218.17  496.53  222.88  497.05     232  500.98   247.2  514.94  253.28  517.36
  265.44  527.53  274.55  533.85  280.63  537.83  283.67  537.72  289.75  541.45
#Mann= 3 , 0 , 0
       0      .1       0   213.7      .1       0  222.88      .1       0
Bank Sta=213.7,222.88
XS Rating Curve= 0 ,0
Exp/Cntr=0.3,0.1

Type RM Length L Ch R = 1 ,1144.899,61.47,47.62,42.47
XS GIS Cut Line= 6
     616989.2595    4333951.2753     616969.7814    4334141.8796
     616965.1512    4334148.2296      616944.646    4334148.4942
     616939.6189    4334145.8483     616913.8531    4334229.0884
#Sta/Elev= 30
       0  540.81   18.25  533.69   24.33  532.32   48.66  522.35   54.74  521.35
   82.11  513.04   85.15  513.04  106.44  506.23  112.53  504.72  115.57   504.6
  127.73   501.1  145.98  499.65  164.23  496.84  179.43  496.83  199.46  497.66
  208.18  496.12  213.99     496  215.15   496.2  222.48  496.89  228.16  496.59
  246.58  498.26  252.56  499.54  255.56  501.11  273.52  515.74  276.51   516.3
  279.51  517.97  291.48  527.41  306.45  536.97  309.44  536.87  315.43  540.56
#Mann= 3 , 0 , 0
       0      .1       0  208.18      .1       0  215.15      .1       0
Bank Sta=208.18,215.15
XS Rating Curve= 0 ,0
Exp/Cntr=0.3,0.1

Type RM Length L Ch R = 1 ,1097.28 ,73.77,71.33,69.22
XS GIS Cut Line= 5
     616963.7536    4333966.6741     616943.1622    4334075.3618
     616922.1593    4334107.0278     616903.1829    4334130.2211
     616876.9701     4334231.258
#Sta/Elev= 30
       0  540.15    6.15  537.78   12.29  536.84   36.87  528.44   43.02  527.61
   49.16  525.65   58.38  522.36   70.67  517.29   73.75   517.4   82.97  513.43
   89.11  510.17   101.4  500.62  104.48  500.29  107.55  498.78  110.62  497.91
  119.39  496.47  142.77  495.96  151.62  494.76  154.61   494.7  156.91  494.99
   163.6  495.74  206.22     495   218.5  497.35  221.57   498.8  227.71  502.97
  239.99  513.28  246.13  517.94   249.2  518.01  276.83  537.16  282.97  539.15
#Mann= 3 , 0 , 0
       0      .1       0  151.62      .1       0  156.91      .1       0
Bank Sta=151.62,156.91
XS Rating Curve= 0 ,0
Exp/Cntr=0.3,0.1

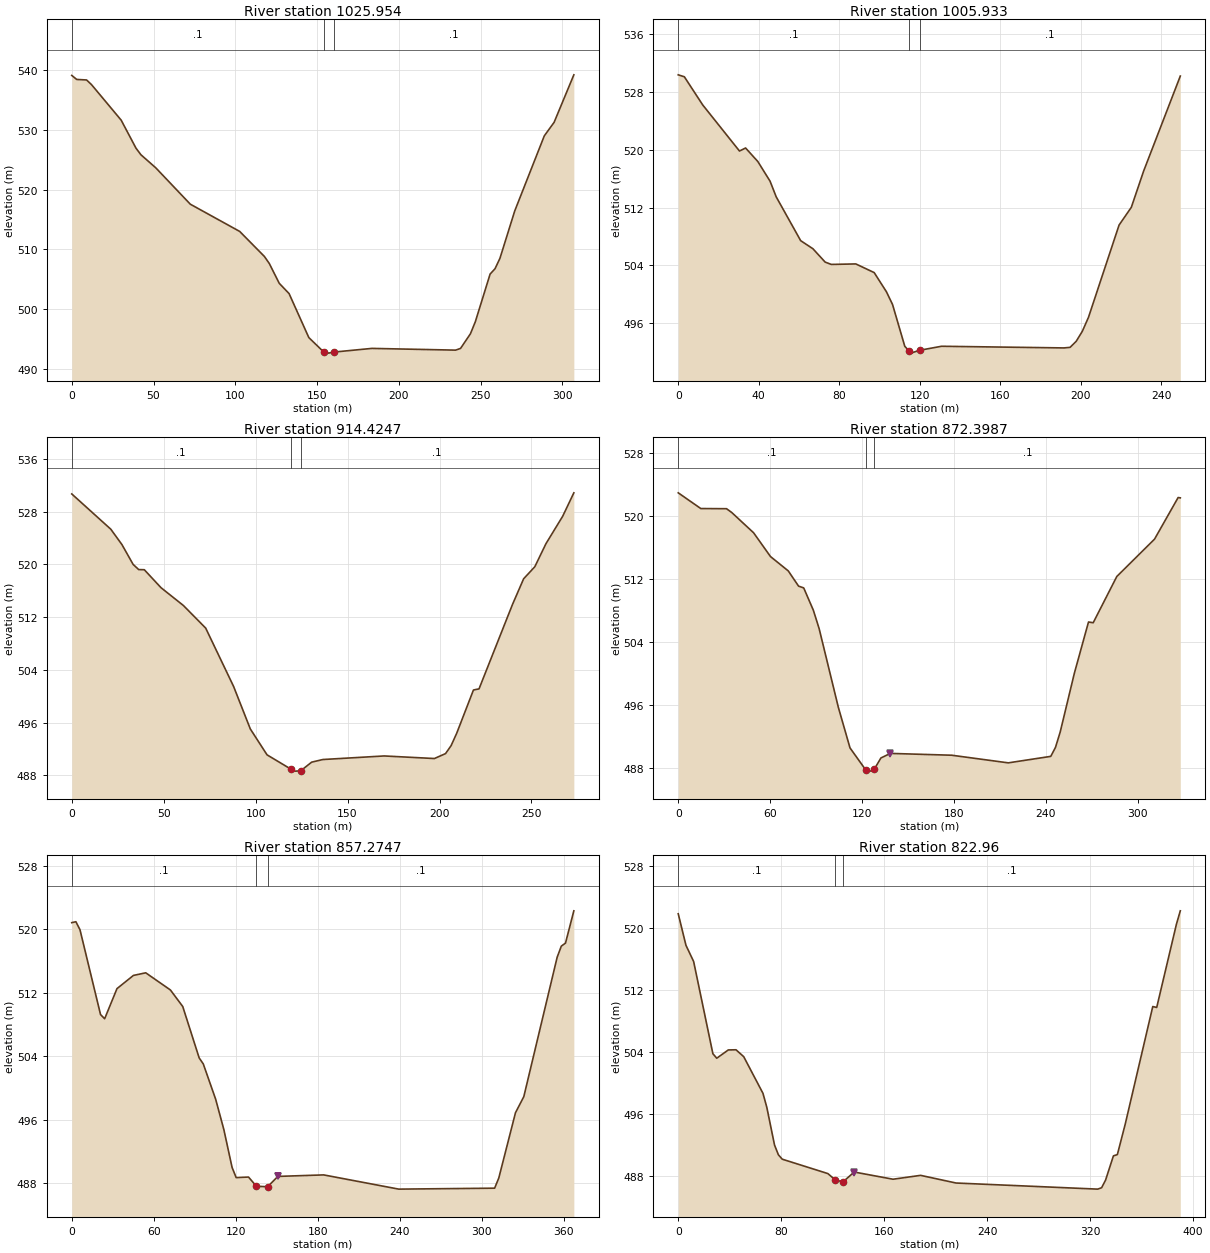
Type RM Length L Ch R = 1 ,1025.954,20.05,20.02,20.31
XS GIS Cut Line= 4
     616906.6273    4333926.0447     616856.3219    4334077.9811
     616856.3837    4334080.3607     616817.7033    4334219.6163
#Sta/Elev= 30
       0  539.06    3.02  538.39    9.06   538.3   12.08  537.52    30.2  531.59
   39.26  526.91   42.28  525.81   51.34  523.63   72.47  517.55  102.67     513
  117.77  508.82  120.79  507.63  126.83  504.34  132.87  502.61  144.95  495.26
  154.01  492.87  157.03  492.67  160.05  492.84  183.51  493.46  234.69  493.17
   237.7  493.46  243.73   495.9  246.74  497.92  255.77  505.88  258.78  506.77
  261.79  508.52  270.82  516.42  288.89  528.96  294.91  531.23  306.96  539.16
#Mann= 3 , 0 , 0
       0      .1       0  154.01      .1       0  160.05      .1       0
Bank Sta=154.01,160.05
XS Rating Curve= 0 ,0
Exp/Cntr=0.3,0.1

Type RM Length L Ch R = 1 ,1005.933,92.67,91.51,90.48
XS GIS Cut Line= 2
     616864.2586    4333960.0671     616806.0616    4334202.6829
#Sta/Elev= 30
       0  530.39    3.04  530.12   12.17  526.22   30.43  519.84   33.47  520.26
   39.55  518.39   45.64  515.66   48.68   513.5   60.85  507.43   66.94  506.31
   73.02  504.46   76.07  504.14   88.24  504.21   97.37  503.01  103.45  500.36
  106.49   498.6  112.58  492.81   114.9  492.09  115.62  491.86   119.9  492.25
  130.83  492.81  191.69  492.58  194.73  492.66  197.77   493.5  200.82  494.89
  203.86  496.81  219.07  509.59  225.16  512.05  231.24  517.04   249.5  530.22
#Mann= 3 , 0 , 0
       0      .1       0   114.9      .1       0   119.9      .1       0
Bank Sta=114.9,119.9
XS Rating Curve= 0 ,0
Exp/Cntr=0.3,0.1

Type RM Length L Ch R = 1 ,914.4247,40.24,42.03,39.53
XS GIS Cut Line= 3
     616768.4907    4333969.0554     616745.6838    4334028.5644
     616749.0438    4334237.8726
#Sta/Elev= 30
       0  530.68   21.24  525.33   27.31  522.99   33.38  519.99   36.42  519.21
   39.45  519.19   48.56  516.46   60.69  513.77   72.83  510.34      88   501.5
    97.1  495.05   106.2  491.12  119.08  488.97  121.37  488.65  124.41  488.68
  130.47  490.01  136.54  490.41  169.91  490.95  197.22  490.56  203.29  491.31
  206.32  492.52  209.35  494.39  218.46  500.95  221.49  501.12  239.69  513.92
  245.76  517.82  251.83  519.64   257.9  523.14     267   527.3  273.06  530.85
#Mann= 3 , 0 , 0
       0      .1       0  119.08      .1       0  124.41      .1       0
Bank Sta=119.08,124.41
XS Rating Curve= 0 ,0
Exp/Cntr=0.3,0.1

Type RM Length L Ch R = 1 ,872.3987,11.77,15.12,21.56
XS GIS Cut Line= 6
     616754.2032    4333964.0283     616707.6994    4334069.2345
     616706.1119    4334076.5371     616708.8107    4334078.7596
     616708.0169    4334083.5221     616694.6718     4334280.206
#Sta/Elev= 30
       0 522.899  14.736 520.903  31.542 520.882  34.904 520.408  49.219 517.828
   60.27 514.807  71.877 512.986  78.599 511.053  81.961 510.826  88.241 508.002
  92.044 505.654 104.557 495.685 112.212 490.509   122.5 487.712 126.197 487.564
  128.06 487.814 132.412 489.237 138.574 489.814 178.632 489.583 215.608 488.614
  243.34 489.438 246.421 490.577 249.503  492.53 258.747 499.989 267.991 506.495
 271.072 506.408 286.479 512.276 311.129  517.02 326.536 522.301  327.96 522.261
#Mann= 3 , 0 , 0
       0      .1       0   122.5      .1       0  128.06      .1       0
Levee=0,,,-1,138.42,489.85,,
Bank Sta=122.5,128.06
XS Rating Curve= 0 ,0
Exp/Cntr=0.3,0.1

Type RM Length L Ch R = 1 ,857.2747,35.99,34.31,34.28
XS GIS Cut Line= 6
     616738.3281    4333942.8616     616698.2644    4334065.7632
     616693.2373    4334068.6736     616691.6498    4334071.4518
     616683.2812     4334080.676     616651.0155    4334294.7581
#Sta/Elev= 30
       0  520.82    3.01  520.94    6.01  519.93   21.04  509.26   24.05  508.73
   33.07  512.52   45.09  514.18   54.11  514.51   72.15  512.35   81.17  510.27
   93.19   503.8    96.2  503.04  105.22  498.62  111.23  494.79  117.24  490.03
  120.25  488.74  129.27  488.81  135.08  487.65  143.26  487.59  150.73  488.89
  184.27  489.08  239.16  487.29  309.29  487.41  312.34  488.69  324.54   496.9
  330.64  498.93  355.03  516.47  358.08  517.87  361.13  518.25  367.23  522.31
#Mann= 3 , 0 , 0
       0      .1       0  135.08      .1       0  143.26      .1       0
Levee=0,,,-1,150.78,488.89,,
Bank Sta=135.08,143.26
XS Rating Curve= 0 ,0
Exp/Cntr=0.3,0.1

Type RM Length L Ch R = 1 ,822.96  ,56.92,52.94,49.7
XS GIS Cut Line= 4
     616721.1302    4333940.2157     616682.6106    4334027.8936
     616651.1996    4334066.4684     616621.9112    4334309.3102
#Sta/Elev= 30
       0  521.85    5.99  517.78   11.97  515.68   26.93  503.76   29.93  503.18
    38.9  504.25   44.89  504.27   50.88  503.38   65.84  498.64   68.83  496.83
   74.82  491.96   77.81   490.7    80.8  490.13  116.25  488.27   122.1  487.44
  127.95  487.19  136.73  488.47  166.91  487.54  188.32  488.04  215.84  487.05
  325.91  486.26  328.96  486.44  332.02  487.42  338.14  490.56  341.19  490.72
  347.31  494.66  368.71  509.86  371.77  509.74  387.06  520.48  390.11  522.23
#Mann= 3 , 0 , 0
       0      .1       0   122.1      .1       0  127.95      .1       0
Levee=0,,,-1,136.3,488.45,,
Bank Sta=122.1,127.95
XS Rating Curve= 0 ,0
Exp/Cntr=0.3,0.1

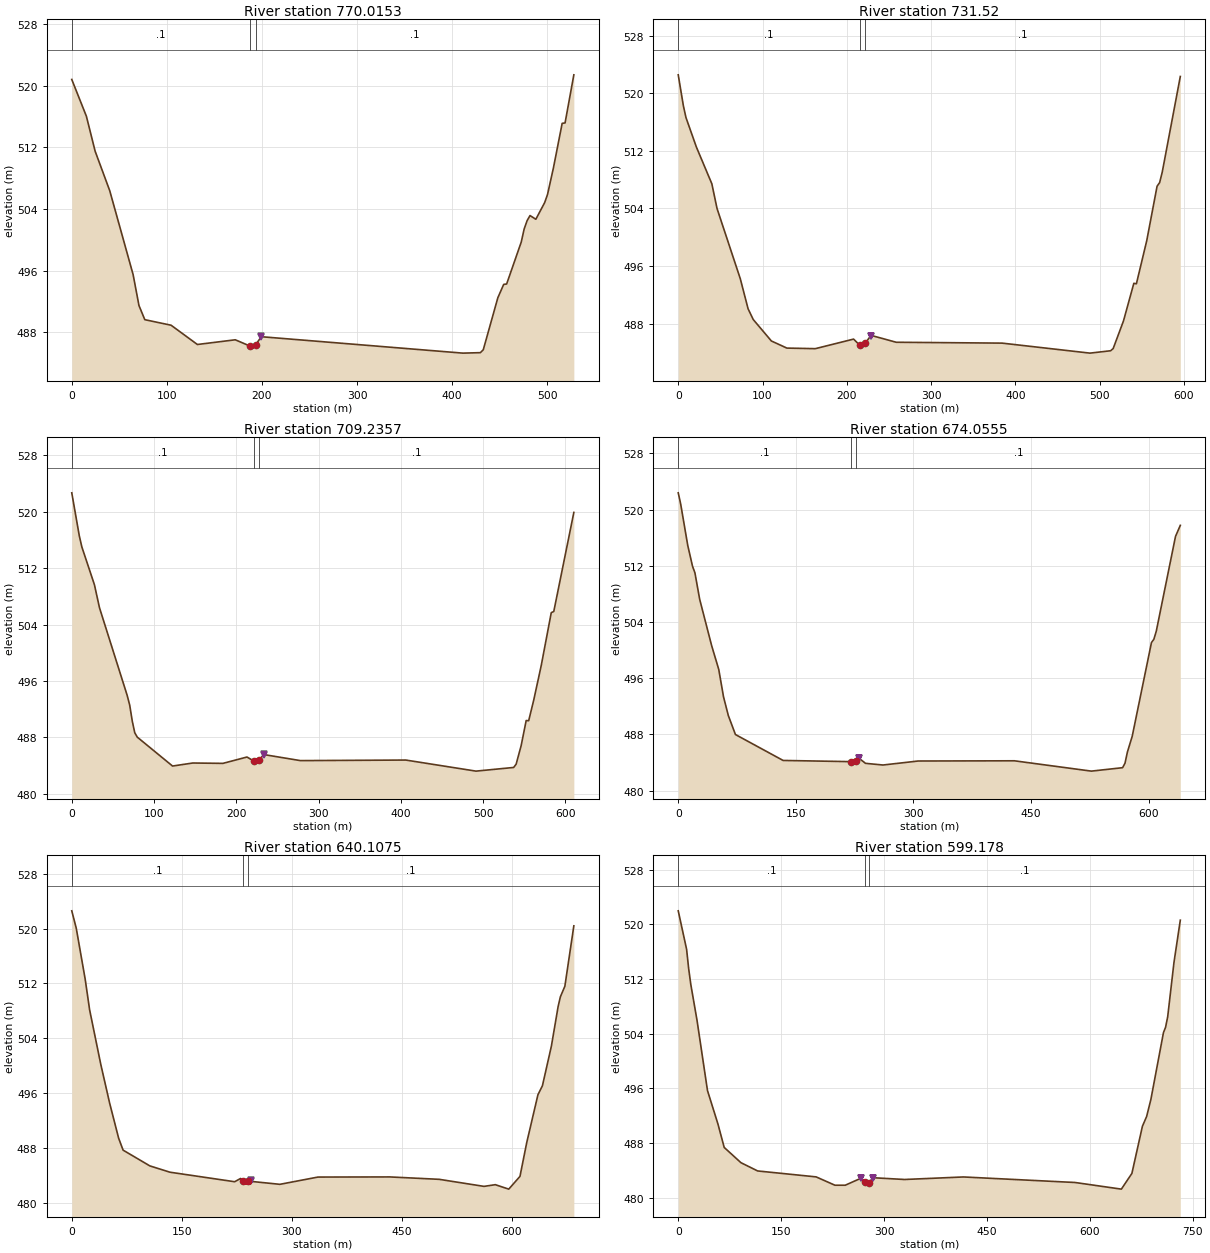
Type RM Length L Ch R = 1 ,770.0153,36.05,38.5,40.93
XS GIS Cut Line= 4
       616696.49    4333866.2859     616614.2696    4334006.8151
     616620.6084    4334058.1586     616570.3174    4334367.5187
#Sta/Elev= 30
       0  520.79   15.36  516.02   24.58  511.48   39.94  506.35   64.51  495.47
   70.66  491.46    76.8  489.62  104.45   488.9   132.1   486.4  171.94  487.01
  187.16  486.21  193.25  486.35  199.33  487.41   411.2  485.28  429.64  485.34
  432.71  485.71  448.08  492.48  454.22   494.2   457.3  494.25  472.66  499.69
  475.73  501.39   478.8  502.46  481.88  503.13  488.02  502.65  497.24   504.8
  500.31  505.87  506.46  509.29  515.68  515.09  518.75  515.15  527.97  521.39
#Mann= 3 , 0 , 0
       0      .1       0  187.16      .1       0  193.25      .1       0
Levee=0,,,-1,199.28,487.48,,
Bank Sta=187.16,193.25
XS Rating Curve= 0 ,0
Exp/Cntr=0.3,0.1

Type RM Length L Ch R = 1 ,731.52  ,22.03,22.28,22.49
XS GIS Cut Line= 5
     616689.2699    4333823.7988     616592.8784    4333998.4519
     616585.1043    4334010.4427     616564.4764    4334050.3001
     616534.5986    4334386.0395
#Sta/Elev= 30
       0  522.57    6.14  518.24    9.21  516.62   21.48  512.55    39.9  507.42
   46.04  503.99   73.66  494.22   82.86  490.06      89  488.56  110.49  485.58
   128.9  484.59  162.66  484.51  208.06  485.84  215.49  484.97  219.76  484.91
  221.72  485.24  228.74  486.36  258.66   485.4  384.29  485.28  488.47  483.89
  512.99  484.22  516.05  484.52  528.31  488.37  540.57  493.59  543.63  493.53
  555.89  499.52  568.14  507.08  571.21   507.6  574.27  509.04  595.72  522.34
#Mann= 3 , 0 , 0
       0      .1       0  215.49      .1       0  221.72      .1       0
Levee=0,,,-1,228.61,486.29,,
Bank Sta=215.49,221.72
XS Rating Curve= 0 ,0
Exp/Cntr=0.3,0.1

Type RM Length L Ch R = 1 ,709.2357,33.69,35.18,35.8
XS GIS Cut Line= 5
     616688.6653    4333822.3001     616580.5563    4333974.7004
     616557.0613    4334014.8643      616544.315    4334044.6696
     616527.7652    4334388.8799
#Sta/Elev= 30
       0  522.68    9.19  516.56   12.25  515.01   27.57  509.64   33.69  506.39
   67.39  493.95   70.45  492.57   73.52  490.34   76.58  488.66   79.64  488.04
  122.53  483.94  147.03  484.37  183.79  484.32  213.03  485.22  221.75  484.62
  227.57  484.77  233.38  485.57     278  484.71  406.08  484.79  491.47  483.22
  537.22  483.74  540.27  484.21  546.36  486.84  552.46  490.39  555.51  490.37
  561.61  493.28  570.76  498.19  582.96  505.69  586.01  505.85  610.41   519.9
#Mann= 3 , 0 , 0
       0      .1       0  221.75      .1       0  227.57      .1       0
Levee=0,,,-1,233.44,485.6,,
Bank Sta=221.75,227.57
XS Rating Curve= 0 ,0
Exp/Cntr=0.3,0.1

Type RM Length L Ch R = 1 ,674.0555,37.53,33.95,33.61
XS GIS Cut Line= 6
     616687.3225    4333820.1702     616553.4431    4333961.3257
     616527.1964     4333993.552     616526.5614    4334012.7079
     616524.9739    4334042.0238     616516.5072    4334397.6774
#Sta/Elev= 30
       0  522.39    3.04  520.85   12.16  514.89   18.24  511.93   21.28  511.01
   27.36  507.23   42.56  500.66   51.68  497.25   57.76  493.35   63.84   490.7
   72.96  487.98  133.75  484.29   220.3  484.12  224.23  483.85   227.2  484.25
  230.17  484.64  238.85  483.88  261.15  483.64   306.1  484.21  428.78  484.24
  526.92  482.77  566.78  483.26  569.85   483.9  572.92  485.49  579.05  487.73
  603.59  501.07  606.65  501.54  609.72  502.68  634.26  516.18  640.39  517.76
#Mann= 3 , 0 , 0
       0      .1       0   220.3      .1       0   227.2      .1       0
Levee=0,,,-1,230.2,484.65,,
Bank Sta=220.3,227.2
XS Rating Curve= 0 ,0
Exp/Cntr=0.3,0.1

Type RM Length L Ch R = 1 ,640.1075,42.44,40.93,39.04
XS GIS Cut Line= 6
      616687.947    4333817.1842     616509.4322    4333954.6132
     616507.0199    4333964.3003     616501.9511    4333971.7428
     616508.7245    4334047.7313     616504.0149    4334412.1691
#Sta/Elev= 30
       0   522.6    6.09  520.08   18.27  512.65   24.36  508.15   39.58   500.2
   51.76   494.5   63.93  489.43   70.02  487.68  106.55  485.38  133.95  484.46
  222.24  483.07  230.28  483.54  234.19  483.17  240.92  483.16  283.95  482.69
  335.88  483.75  433.89  483.77  501.27  483.42  562.52  482.39  577.84  482.64
  596.21  481.99  611.53  483.85  620.71  488.76  636.03  495.76  642.15  497.07
   654.4  502.86  663.59  508.64  666.65  510.05  672.78  511.59  685.03  520.41
#Mann= 3 , 0 , 0
       0      .1       0  234.19      .1       0  240.92      .1       0
Levee=0,,,-1,244.24,483.27,,
Bank Sta=234.19,240.92
XS Rating Curve= 0 ,0
Exp/Cntr=0.3,0.1

Type RM Length L Ch R = 1 ,599.178 ,52.37,50.54,50.77
XS GIS Cut Line= 6
     616687.2557    4333814.5756     616477.1827    4333931.8656
     616466.9301    4333948.4021     616464.0726    4333971.8972
     616469.0203    4334057.7811     616493.2298     4334418.938
#Sta/Elev= 30
       0  521.99   12.18  516.37   15.23  513.51   18.27  511.25   27.41  505.95
   42.64  495.69   57.87   490.8      67  487.37   91.37  485.14  115.73  483.93
  201.01  483.06  228.42  481.84  243.38  481.84  265.97  482.85  271.89  482.38
  277.81   482.2  283.72  482.94  329.81  482.68  415.76  483.05  578.34  482.24
  645.83  481.27  661.16  483.57   676.5  490.47  682.64   491.9  688.77  494.36
  707.18  504.18  710.24  504.95  713.31  506.48  722.51  514.46  731.72  520.62
#Mann= 3 , 0 , 0
       0      .1       0  271.89      .1       0  277.81      .1       0
Levee=-1,265.89,482.86,-1,283.79,482.95,,
Bank Sta=271.89,277.81
XS Rating Curve= 0 ,0
Exp/Cntr=0.3,0.1