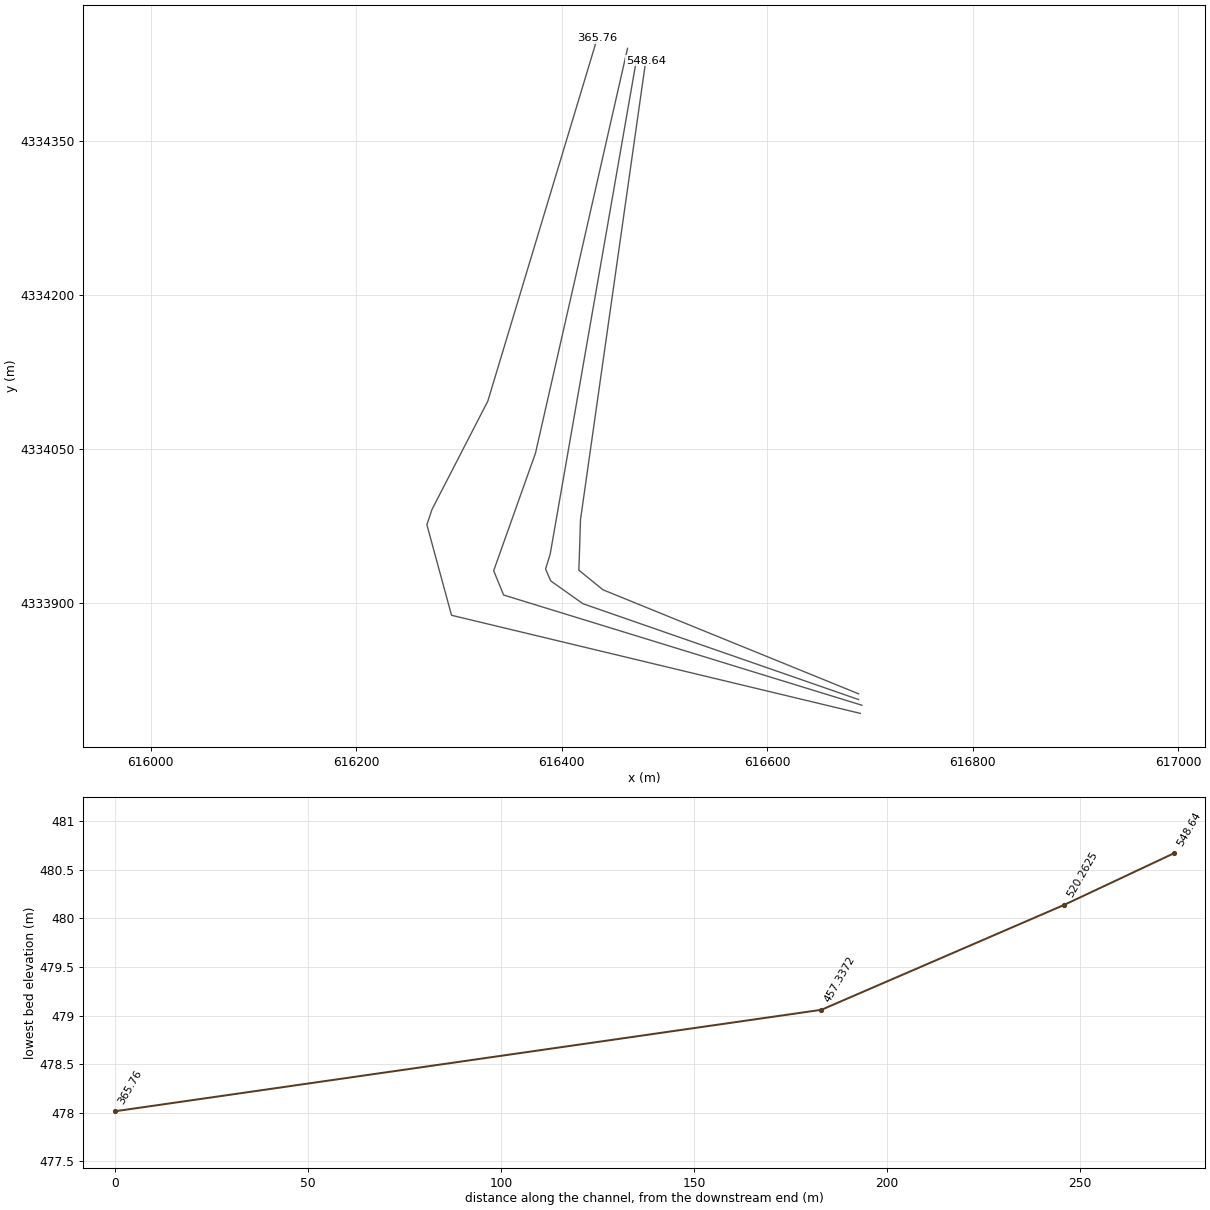
HEC-RAS study DryRun.prj: DryRun

--- DryRun.g01 (geometry) --- (continued)

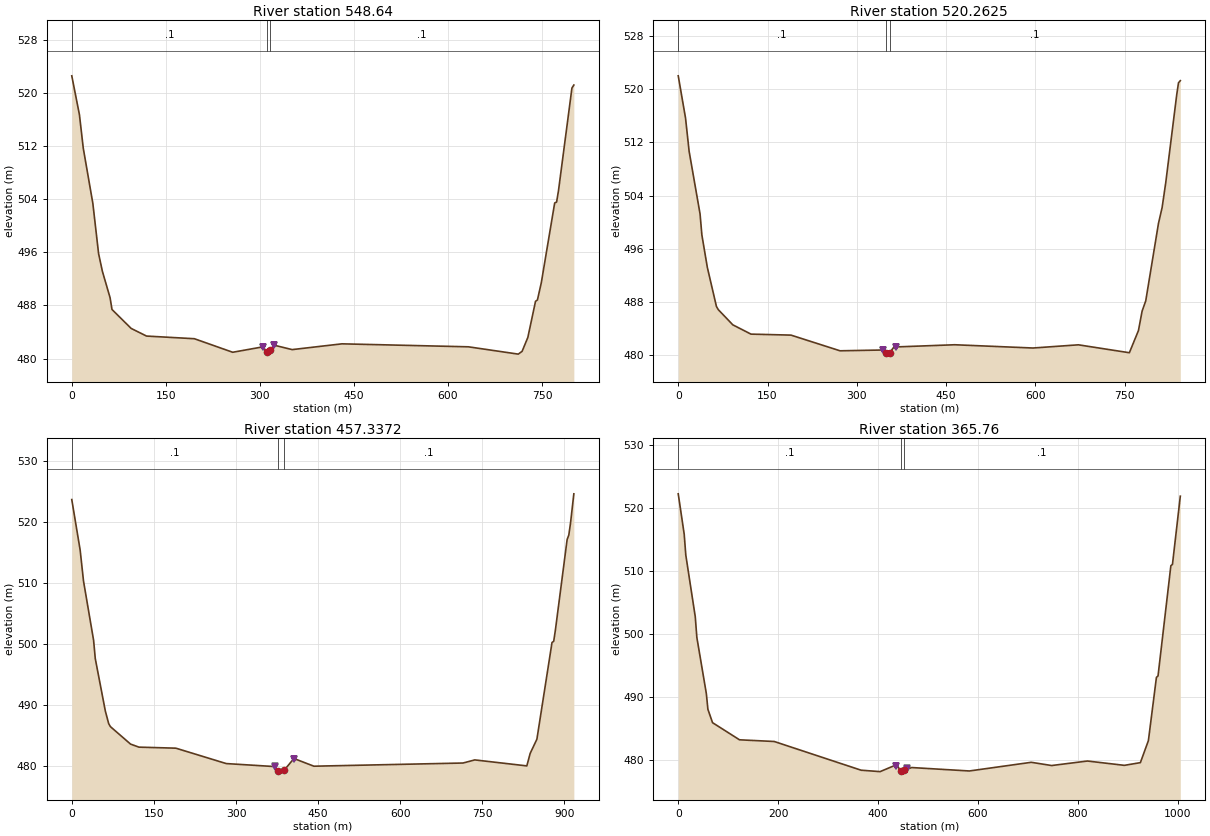
Type RM Length L Ch R = 1 ,548.64  ,31.12,28.38,28.27
XS GIS Cut Line= 6
     616689.0053    4333811.2311     616440.0749    4333912.7296
      616416.593    4333931.9119     616417.0782    4333943.6974
     616418.2351    4333981.1039     616481.7898    4334428.8379
#Sta/Elev= 30
       0  522.57   12.22  516.72   18.33  511.68    33.6  503.37   42.77   495.8
   48.88  493.12    61.1  489.16   64.15  487.39    94.7  484.54  119.14  483.39
  195.51  482.99  256.61  480.95  305.05  481.77  310.94  481.01   316.7   481.3
  322.46  482.02  351.42  481.35  430.87  482.22  632.54  481.77  711.98  480.67
  718.09  481.09  727.26  483.19  739.48  488.62  742.54  488.83  748.65  491.39
  770.04  503.43  773.09  503.56  776.15  505.31  797.54  520.73  800.59  521.18
#Mann= 3 , 0 , 0
       0      .1       0  310.94      .1       0   316.7      .1       0
Levee=-1,305.01,481.78,-1,322.46,482.03,,
Bank Sta=310.94,316.7
XS Rating Curve= 0 ,0
Exp/Cntr=0.3,0.1

Type RM Length L Ch R = 1 ,520.2625,58.13,62.93,65.62
XS GIS Cut Line= 6
     616688.8498    4333805.6922     616420.6253    4333899.1406
     616389.2721    4333921.3656     616384.2483    4333932.9676
     616388.7463    4333947.5197     616473.2367    4334432.7775
#Sta/Elev= 30
       0  522.01   12.22  515.68   18.32  510.64   36.65  501.23    39.7  498.07
   48.87  493.19   64.14  487.32   67.19  486.84   91.62  484.55  122.17  483.15
  189.36     483  271.82  480.64   343.3  480.76  348.29  480.34  353.46  480.14
  355.33  480.37  362.21  481.21  464.29  481.55  595.69  481.06  672.08  481.54
  757.65  480.35  772.93  483.69  779.04  486.61  785.15  488.15  806.54  499.81
  812.65  502.19  818.76  505.94   837.1  519.11  840.15  520.96  843.21  521.28
#Mann= 3 , 0 , 0
       0      .1       0  348.29      .1       0  355.33      .1       0
Levee=-1,343.1,480.76,-1,365.06,481.22,,
Bank Sta=348.29,355.33
XS Rating Curve= 0 ,0
Exp/Cntr=0.3,0.1

Type RM Length L Ch R = 1 ,457.3372,111.97,183.02,187.16
XS GIS Cut Line= 5
     616692.1803    4333800.1186      616343.415    4333907.6185
      616333.732    4333931.3342      616374.425    4334045.9917
     616464.0197    4334440.8169
#Sta/Elev= 30
       0  523.67   15.33   515.4   21.47  510.32   39.87  500.64   42.94  497.64
   61.34  489.05   67.47  486.99   70.54  486.51  107.34  483.65  122.67  483.15
  190.15  482.98  282.15  480.46  370.65  479.97  376.99   479.3  381.99  479.06
  387.73  479.35  405.78  481.29  442.28  480.03  714.67  480.55  736.14  481.06
  831.22  480.08  837.35  482.13  849.62  484.45  877.23  500.28  880.29  500.47
  883.36  502.28  904.83  517.13   907.9  517.86  910.97  519.77   917.1  524.61
#Mann= 3 , 0 , 0
       0      .1       0  376.99      .1       0  387.73      .1       0
Levee=-1,370.75,479.99,-1,405.85,481.29,,
Bank Sta=376.99,387.73
XS Rating Curve= 0 ,0
Exp/Cntr=0.3,0.1

Type RM Length L Ch R = 1 ,365.76  ,83.87,365.76,182.37
XS GIS Cut Line= 6
     616690.5928    4333792.1811     616292.7213     4333887.864
     616268.7365    4333976.1085     616273.6713    4333991.0517
     616328.0236    4334096.7256     616434.5186    4334450.6065
#Sta/Elev= 30
       0 522.194  11.957 515.778  15.119 512.488   34.09 502.679  37.252 499.409
  56.224   490.5  59.385 487.989  68.685 485.866 122.624 483.147 192.186 482.878
 366.092  478.32 404.035 478.096 432.306 479.038 438.757 479.021  445.39 478.154
 448.433 478.016  451.42 478.317 467.541 478.742 582.592 478.199 706.658 479.576
 747.299 479.062 819.024 479.778 892.899 479.093 924.969 479.522 941.021 483.023
 957.074 493.058 960.284 493.284 985.968 510.778 989.178 510.9951004.878 521.819
#Mann= 3 , 0 , 0
       0      .1       0  445.39      .1       0  451.42      .1       0
Levee=-1,436.3,479.02,-1,457.42,478.68,,
Bank Sta=445.39,451.42
XS Rating Curve= 0 ,0
Exp/Cntr=0.3,0.1
LCMann Table=0

Chan Stop Cuts=-1
Use User Specified Reach Order=0
Composite Channel Slope=5